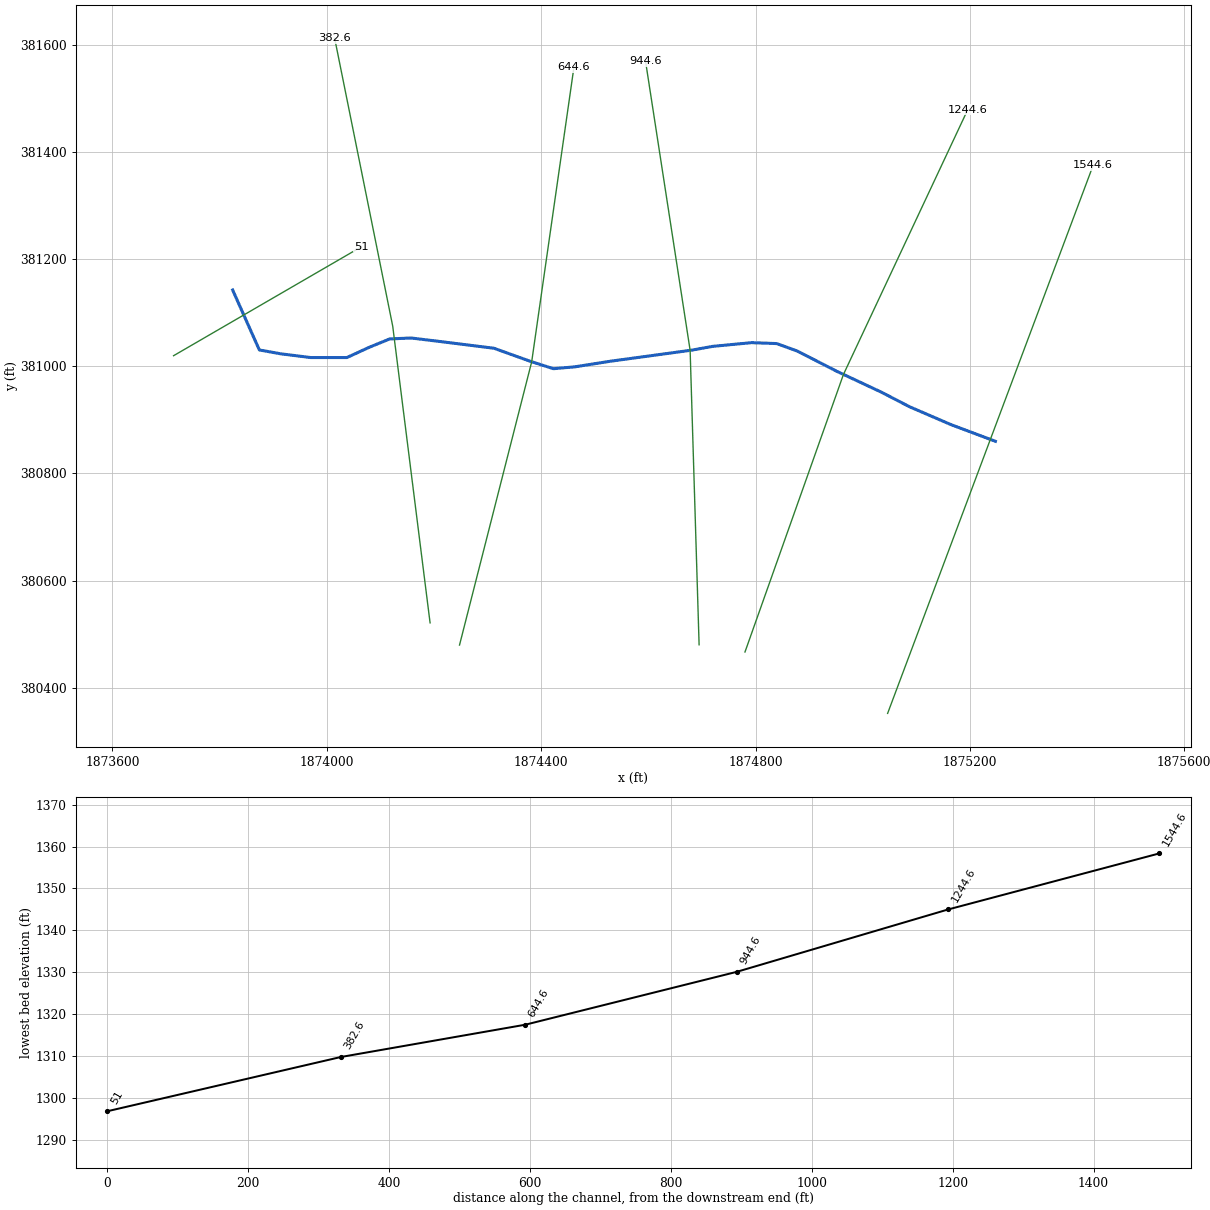
--- LFkArmstCk.prj (project) ---

Proj Title=LFkArmstCk
Current Plan=p01
Default Exp/Contr=0,0
English Units
Geom File=g01
Flow File=f01
Plan File=p01
BEGIN DESCRIPTION:
END DESCRIPTION:
DSS Export Rating Curves= 0
DSS Export Rating Curve Sorted= 0
DSS Export Volume Flow Curves= 0
DXF OffsetX= 0
DXF OffsetY= 0
DXF ScaleX= 0
DXF ScaleY= 0

--- LFkArmstCk.p01 (plan) ---

Plan Title=Floodplain
Program Version=4.00
Geom File=g01
Flow File=f01
K Sum by GR=0
Std Step Tol=0.01
Critical Tol=0.01
Num of Std Step Trials=20
Max Error Tol=0.3
Flow Tol Ratio=0.001
Split Flow NTrial=30
Split Flow Tol=0.02
Split Flow Ratio=0.02
Log Output Level=0
Friction Slope Method=1
Unsteady Friction Slope Method=2
Unsteady Bridges Friction Slope Method=1
Global Log Level=0
CheckData=False
Run HTab=0
Run UNet=0
Run PostProcess=0
UNET Theta=0
UNET Theta Warmup=0
UNET ZTol=0
UNET ZSATol=0
UNET MxIter=0
UNET MaxInSteps=0
UNET DtIC=0
UNET DtMin=0
UNET MaxCRTS=0
UNET WFStab=0
UNET SFStab=0
UNET WFX=0
UNET SFX=0
UNET DSS MLevel=0
UNET DZMax Abort=0
UNET Convert EG Bridges=0
UNET Use Existing IB Tables=0
UNET Froude Limit=0
UNET Froude Power=0
Write IC File=0
Echo Input=False
Echo Output=False
Write Detailed=0

--- LFkArmstCk.f01 (steady flow) ---

Flow Title=NFF Regression Equation
Program Version=4.00
Number of Profiles=1
Profile Names=P100yr
River Rch & RM=LFkArmstCk,Main      ,1544.6
894.6682
River Rch & RM=LFkArmstCk,Main      ,382.6
930.1523
Boundary for River Rch & Prof#=LFkArmstCk,Main      ,1
Up Type=0
Dn Type=3
Dn Slope=0.036796

--- LFkArmstCk.g01 (geometry) ---

Geom Title=USGS 3m DEM
Program Version=4.00

River Reach=LFkArmstCk     ,Main
Reach XY= 24
     1875247.581      380859.896     1875164.248      380891.146
     1875087.859      380924.132     1875034.040      380951.910
     1874952.443      380990.104     1874877.790      381028.299
     1874839.595      381042.187     1874792.720      381043.924
     1874719.804      381036.979     1874681.609      381030.035
     1874528.832      381009.201     1874462.859      380998.785
     1874422.929      380995.313     1874379.526      381009.201
     1874311.818      381033.507     1874214.595      381045.660
     1874157.304      381052.604     1874117.373      381050.868
     1874079.179      381035.243     1874037.512      381016.146
     1873969.804      381016.146     1873914.248      381023.090
     1873874.157      381030.278     1873824.336      381142.169

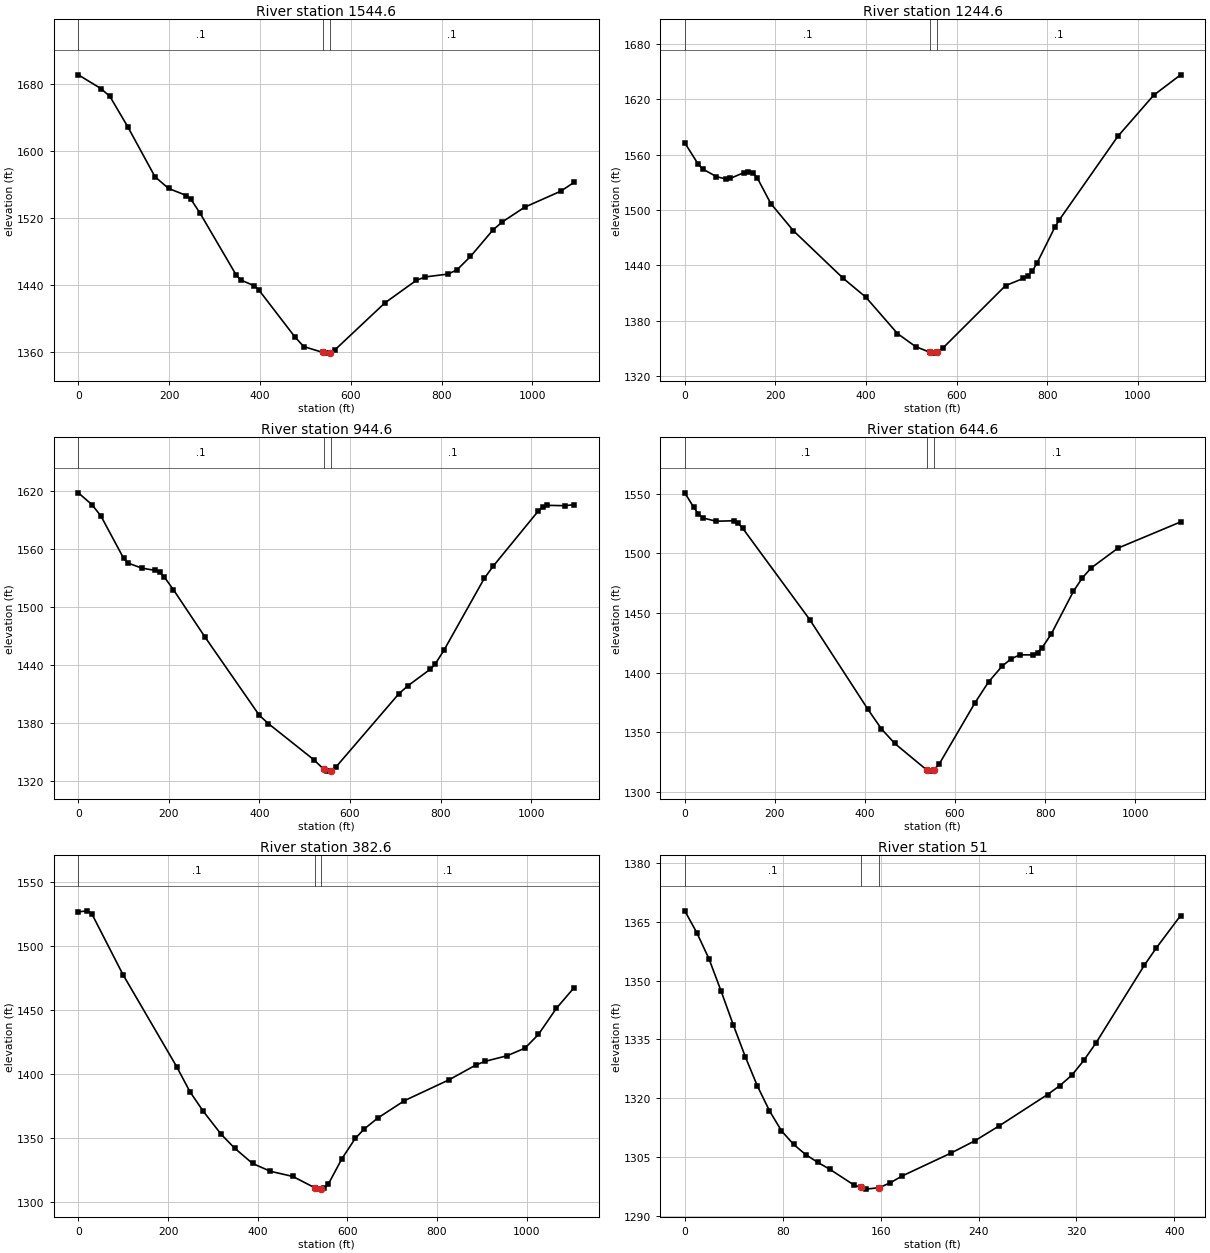
Type RM Length L Ch R = 1 ,1544.6,299.7,300,298.2
XS GIS Cut Line= 3
     1875046.505      380352.171     1875238.218      380863.407
     1875429.932      381374.643
#Sta/Elev= 30
       0 1691.36    49.6 1674.97    69.5 1665.57   109.2 1628.85   168.8 1569.44
   198.6 1555.43   238.2 1546.93   248.2 1542.31   268.0 1525.84   347.4 1452.07
   357.4 1445.91   387.2 1439.04   397.1 1434.27   476.5 1378.07   496.4 1366.18
   538.5 1359.22   546.0 1358.36   553.5 1358.80   565.8 1362.61   675.0 1418.38
   744.6 1445.55   764.4 1449.55   814.0 1452.94   833.9 1457.95   863.7 1474.03
   913.3 1505.82   933.2 1515.11   982.8 1532.92  1062.2 1552.05  1092.0 1562.76
#Mann= 3 , 0 , 0
       0     0.1       0   538.5   0.045       0   553.5     0.1       0
Bank Sta=   538.5,   553.5
Exp/Cntr=0.3,0.1

Type RM Length L Ch R = 1 ,1244.6,291.3,300,313.3
XS GIS Cut Line= 3
     1874780.336      380466.707     1874964.095      380984.650
     1875195.825      381478.339
#Sta/Elev= 30
       0 1572.60    30.0 1549.22    40.0 1544.18    70.0 1536.05    89.9 1533.61
    99.9 1534.05   129.9 1540.29   139.9 1541.56   149.9 1540.42   159.9 1534.83
   189.8 1506.98   239.8 1477.49   349.7 1426.02   399.7 1405.62   469.6 1366.21
   509.6 1352.08   542.1 1345.72   549.6 1344.99   557.1 1346.01   569.4 1350.22
   708.2 1418.04   747.9 1425.94   757.8 1428.73   767.7 1434.16   777.6 1442.34
   817.3 1481.44   827.2 1489.40   956.1 1579.61  1035.4 1624.21  1094.9 1646.29
#Mann= 3 , 0 , 0
       0     0.1       0   542.1   0.045       0   557.1     0.1       0
Bank Sta=   542.1,   557.1
Exp/Cntr=0.3,0.1

Type RM Length L Ch R = 1 ,944.6,306.6,300.1,293.4
XS GIS Cut Line= 3
     1874694.732      380480.138     1874677.980      381029.540
     1874594.852      381568.621
#Sta/Elev= 30
       0 1617.95    30.0 1605.74    50.0 1593.92    99.9 1550.34   109.9 1545.30
   139.9 1540.11   169.9 1537.69   179.9 1535.69   189.9 1530.84   209.9 1517.85
   279.8 1468.76   399.8 1387.82   419.7 1379.28   519.7 1342.04   542.2 1332.02
   549.7 1330.12   557.2 1330.62   569.5 1334.65   708.3 1410.35   728.2 1418.48
   777.8 1435.67   787.7 1440.51   807.5 1455.14   896.8 1529.63   916.6 1542.29
  1015.8 1599.10  1025.7 1603.25  1035.6 1605.01  1075.3 1604.63  1095.1 1605.79
#Mann= 3 , 0 , 0
       0     0.1       0   542.2   0.045       0   557.2     0.1       0
Bank Sta=   542.2,   557.2
Exp/Cntr=0.3,0.1

Type RM Length L Ch R = 1 ,644.6,253.4,261.8,267.8
XS GIS Cut Line= 3
     1874247.680      380479.712     1874382.355      381008.296
     1874461.209      381558.221
#Sta/Elev= 30
       0 1550.75    19.8 1538.57    29.8 1533.32    39.7 1529.76    69.4 1526.95
   109.1 1527.35   119.0 1525.05   128.9 1520.87   277.7 1444.35   406.6 1369.33
   436.4 1353.03   466.1 1340.72     538 1318.28   545.5 1317.52     553 1318.34
   565.3 1323.72   644.7 1374.98   674.4 1392.21   704.2 1405.32   724.0 1411.48
   743.9 1414.97   773.6 1414.93   783.6 1416.93   793.5 1421.02   813.3 1432.13
   862.9 1468.16   882.8 1479.52   902.6 1487.88   962.1 1504.45  1101.0 1526.36
#Mann= 3 , 0 , 0
       0     0.1       0     538   0.045       0     553     0.1       0
Bank Sta=     538,     553
Exp/Cntr=0.3,0.1

Type RM Length L Ch R = 1 ,382.6,359.6,331.5,303
XS GIS Cut Line= 3
     1874192.736      380521.054     1874123.043      381074.571
     1874014.682      381611.772
#Sta/Elev= 30
       0 1526.35    19.9 1527.18    29.9 1524.98    99.6 1477.34   219.2 1405.56
   249.1 1385.78   278.9 1370.50   318.8 1352.54   348.7 1341.78   388.5 1329.89
   428.4 1323.74   478.2 1319.75   526.9 1310.98   538.0 1309.82   541.9 1310.04
   547.9 1310.38   557.9 1313.94   587.8 1333.52   617.7 1349.47   637.6 1356.77
   667.5 1365.24   727.3 1378.90   826.9 1395.21   886.7 1406.76   906.6 1409.57
   956.4 1413.99   996.3 1419.96  1026.2 1430.62  1066.0 1450.92  1105.9 1467.24
#Mann= 3 , 0 , 0
       0     0.1       0   526.9   0.045       0   541.9     0.1       0
Bank Sta=   526.9,   541.9
Exp/Cntr=0.3,0.1

Type RM Length L Ch R = 1 ,51,53.4,51,48.6
XS GIS Cut Line= 2
     1873714.124      381019.570     1874064.529      381222.843
#Sta/Elev= 30
       0 1367.74     9.9 1362.11    19.8 1355.49    29.6 1347.35    39.5 1338.80
    49.4 1330.62    59.3 1323.15    69.2 1316.82    79.0 1311.73    88.9 1308.27
    98.8 1305.68   108.7 1303.69   118.6 1301.92   138.3 1297.92   143.9 1297.34
   148.2 1296.89   158.9 1297.26   168.0 1298.53   177.8 1300.27   217.4 1306.06
   237.1 1309.21   256.9 1313.00   296.4 1320.97   306.3 1323.21   316.2 1325.89
   326.0 1329.66   335.9 1334.09   375.5 1353.91   385.3 1358.32   405.1 1366.54
#Mann= 3 , 0 , 0
       0     0.1       0   143.9   0.045       0   158.9     0.1       0
Bank Sta=   143.9,   158.9
Exp/Cntr=0.3,0.1